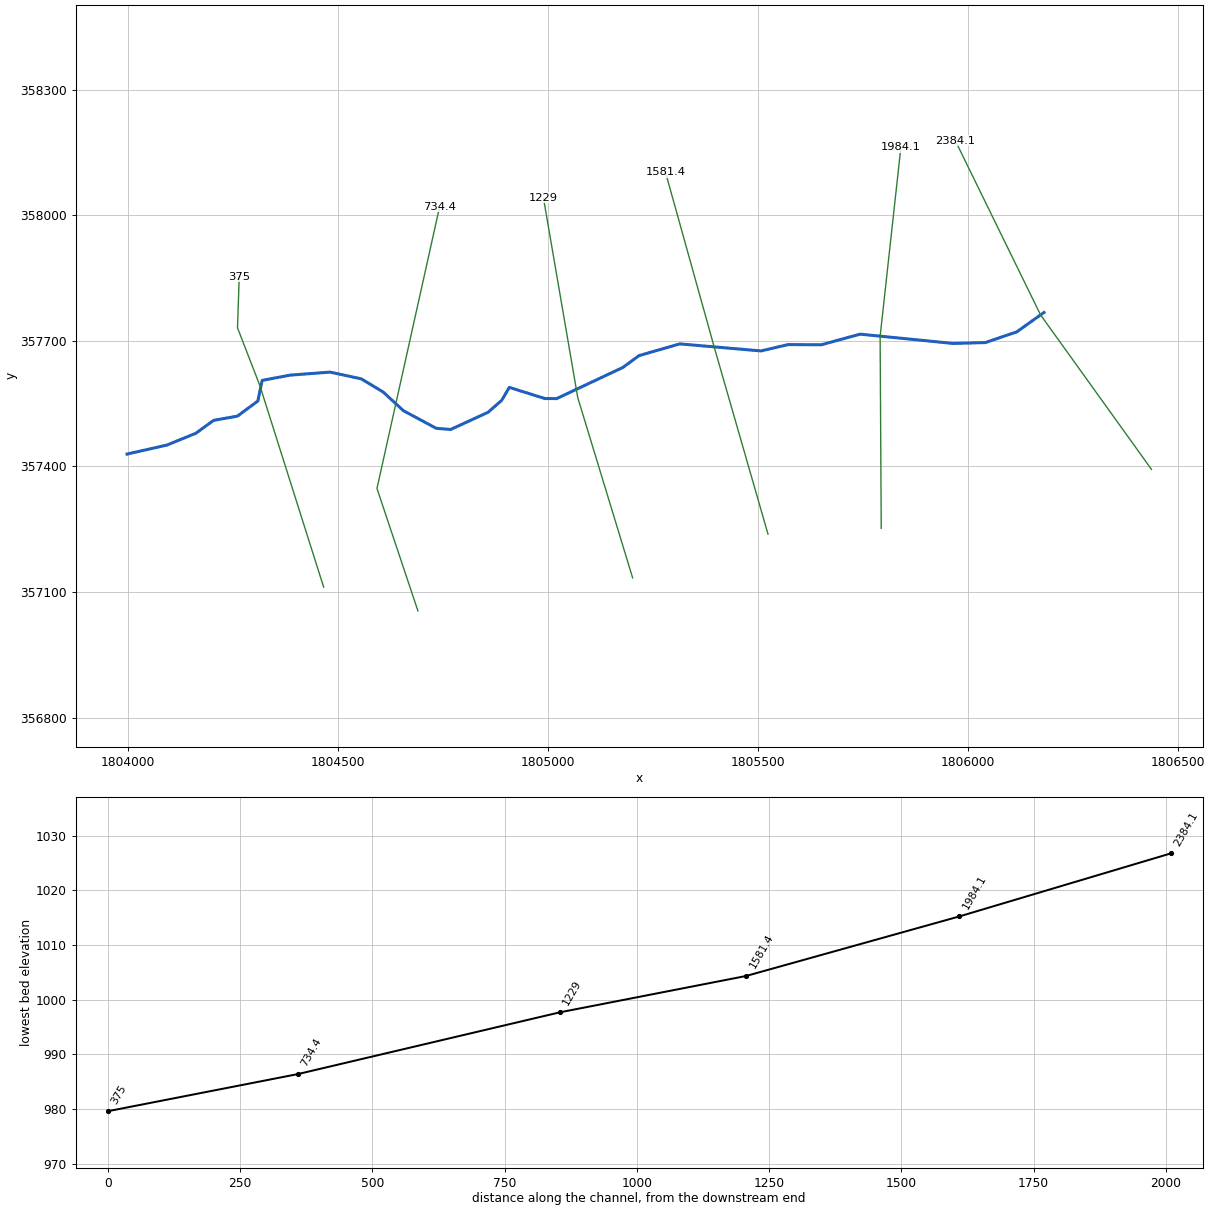
--- RbnRn.prj (project) ---

Proj Title=RbnRn
Current Plan=p01
Geom File=g01
Flow File=f01
Plan File=p01
DSS Export Rating Curves=0
DSS Export Rating Curve Sorted=0
DSS Export Volume Flow Curves=0
DXF OffsetX=0
DXF OffsetY=0
DXF ScaleX=0
DXF ScaleY=0

--- RbnRn.p01 (plan) ---

Plan Title=Floodplain
Program Version=4.00
Geom File=g01
Flow File=f01
K Sum by GR=0
Std Step Tol=0.01
Critical Tol=0.01
Num of Std Step Trials=20
Max Error Tol=0.3
Flow Tol Ratio=0.001
Split Flow NTrial=30
Split Flow Tol=0.02
Split Flow Ratio=0.02
Log Output Level=0
Friction Slope Method=1
Unsteady Friction Slope Method=2
Unsteady Bridges Friction Slope Method=1
Global Log Level=0
CheckData=False
Run HTab=0
Run UNet=0
Run PostProcess=0
UNET Theta=0
UNET Theta Warmup=0
UNET ZTol=0
UNET ZSATol=0
UNET MxIter=0
UNET MaxInSteps=0
UNET DtIC=0
UNET DtMin=0
UNET MaxCRTS=0
UNET WFStab=0
UNET SFStab=0
UNET WFX=0
UNET SFX=0
UNET DSS MLevel=0
UNET DZMax Abort=0
UNET Convert EG Bridges=0
UNET Use Existing IB Tables=0
UNET Froude Limit=0
UNET Froude Power=0
Write IC File=0
Echo Input=False
Echo Output=False
Write Detailed=0

--- RbnRn.f01 (steady flow) ---

Flow Title=NFF Regression Equation
Program Version=4.00
Number of Profiles=1
Profile Names=P100yr
River Rch & RM=RbnRn,Main      ,2384.1
704.7033
River Rch & RM=RbnRn,Main      ,1984.1
772.2763
River Rch & RM=RbnRn,Main      ,375
808.5590
Boundary for River Rch & Prof#=RbnRn,Main      ,1
Up Type=0
Dn Type=3
Dn Slope=0.018693

--- RbnRn.g01 (geometry) ---

Geom Title=USGS 3m DEM
Program Version=4.00

River Reach=RbnRn     ,Main
Reach XY= 30
     1806180.847      357767.696     1806116.055      357721.338
     1806041.366      357695.805     1805964.744      357693.731
     1805743.248      357715.913     1805650.436      357690.497
     1805571.843      357691.002     1805507.251      357675.846
     1805313.923      357692.660     1805217.072      357664.708
     1805178.561      357636.379     1805020.937      357561.985
     1804992.737      357562.167     1804908.256      357588.723
     1804889.932      357557.640     1804857.525      357529.211
     1804768.585      357488.203     1804734.344      357490.989
     1804656.068      357533.138     1804607.996      357577.657
     1804555.818      357609.196     1804481.348      357625.248
     1804386.617      357618.045     1804320.006      357605.470
     1804309.656      357556.139     1804261.062      357520.062
     1804204.546      357510.048     1804162.043      357479.121
     1804093.343      357450.990     1803998.304      357429.463

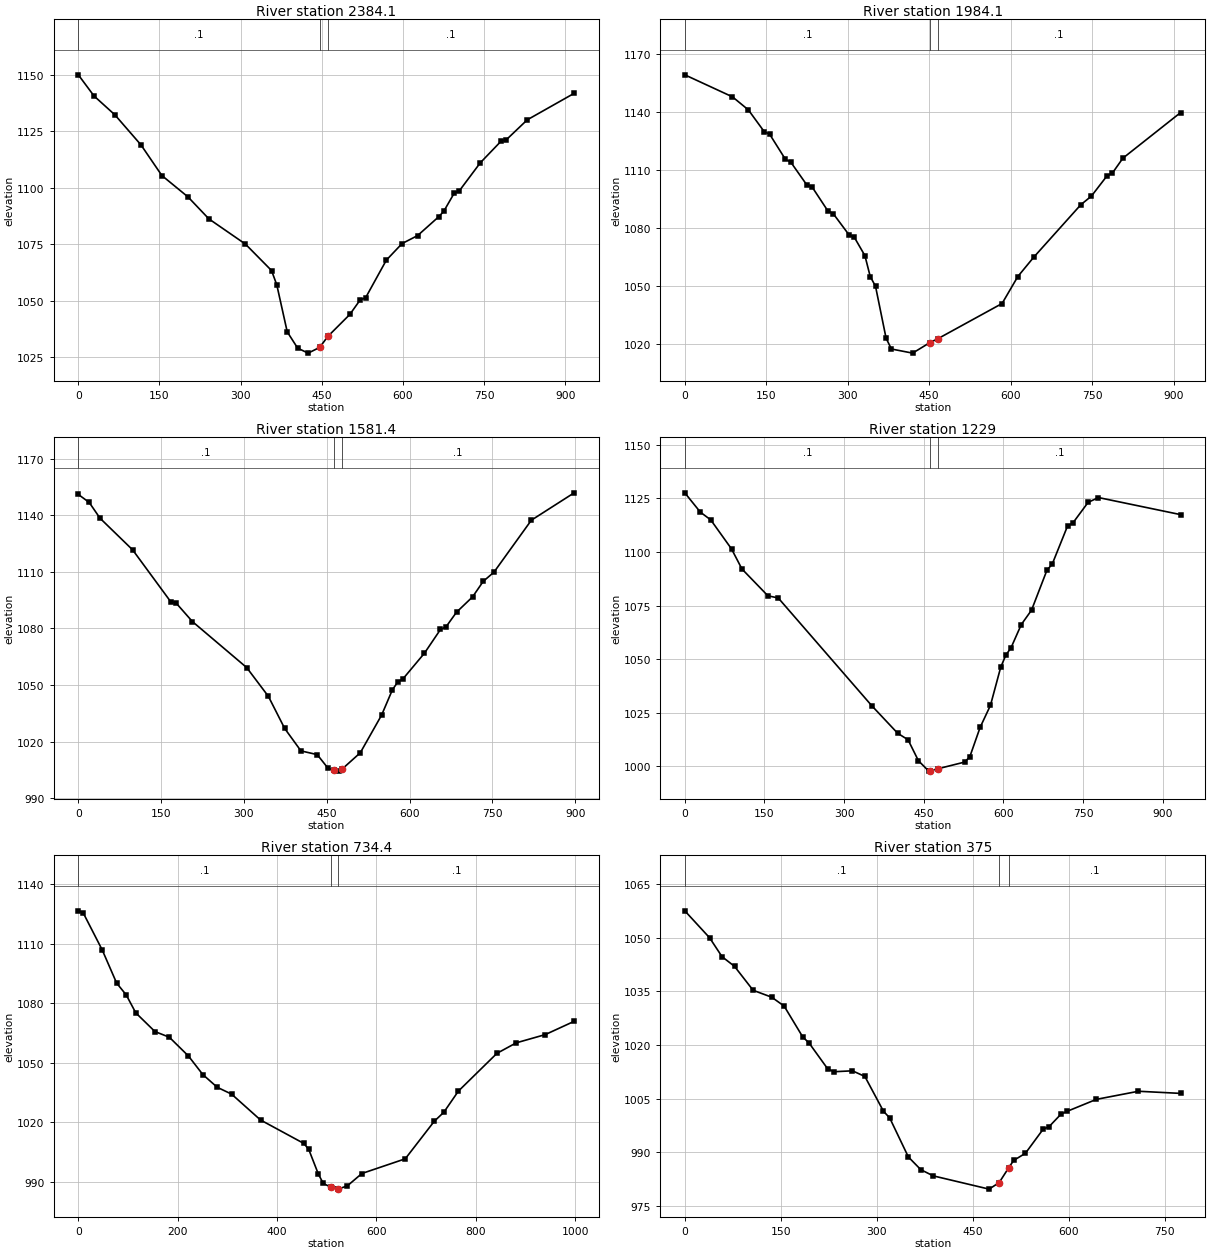
Type RM Length L Ch R = 1 ,2384.1,413.935,400,387.272
XS GIS Cut Line= 3
     1806436.668      357392.962     1806172.714      357761.877
     1805969.873      358177.891
#Sta/Elev= 30
       0 1150.10    29.0 1140.73    67.6 1132.35   115.8 1119.03   154.4 1105.46
   202.7 1095.97   241.3 1086.24   308.8 1075.07   357.1 1063.34   366.8 1056.99
   386.1 1036.16   405.4 1028.93   424.7 1026.73   446.1 1029.27   461.1 1034.13
   501.8 1043.88   521.1 1050.39   530.8 1051.21   569.3 1067.96   598.3 1075.29
   627.2 1078.86   665.7 1087.11   675.4 1089.60   694.7 1097.64   704.3 1098.72
   742.9 1111.10   781.5 1120.73   791.1 1121.34   829.7 1130.15   916.4 1141.90
#Mann= 3 , 0 , 0
       0     0.1       0   446.1   0.045       0   461.1     0.1       0
Bank Sta=   446.1,   461.1
Exp/Cntr=0.3,0.1

Type RM Length L Ch R = 1 ,1984.1,396.048,402.783,411.964
XS GIS Cut Line= 3
     1805793.457      357252.283     1805790.827      357710.704
     1805840.278      358162.400
#Sta/Elev= 30
       0 1159.22    87.8 1147.82   117.0 1141.08   146.3 1129.78   156.1 1128.53
   185.3 1115.46   195.1 1114.04   224.3 1102.37   234.1 1101.29   263.4 1088.78
   273.1 1087.43   302.4 1076.39   312.1 1075.14   331.6 1065.63   341.4 1054.82
   351.1 1049.81   370.6 1022.88   380.4 1017.33   419.4 1015.20   450.9 1020.60
   465.9 1022.66   584.1 1040.88   613.1 1054.84   642.1 1064.75   729.1 1092.01
   748.5 1096.44   777.5 1107.02   787.1 1108.34   806.5 1116.08   912.8 1139.70
#Mann= 3 , 0 , 0
       0     0.1       0   450.9   0.045       0   465.9     0.1       0
Bank Sta=   450.9,   465.9
Exp/Cntr=0.3,0.1

Type RM Length L Ch R = 1 ,1581.4,355.102,352.334,349.178
XS GIS Cut Line= 3
     1805523.956      357238.156     1805396.647      357682.532
     1805279.986      358102.483
#Sta/Elev= 30
       0 1150.96    19.7 1146.73    39.3 1138.36    98.4 1121.58   167.2 1094.16
   177.0 1093.45   206.5 1083.62   304.9 1059.22   344.2 1043.97   373.7 1026.97
   403.2 1015.05   432.7 1013.07   452.4 1005.81   462.9 1004.75   471.9 1004.32
   477.9 1005.44   510.7 1014.04   549.4 1034.06   568.8 1047.38   578.5 1051.53
   588.2 1053.28   626.9 1066.82   656.0 1079.42   665.7 1080.67   685.0 1088.54
   714.1 1096.68   733.5 1104.94   752.8 1109.76   820.6 1137.32   898.1 1151.82
#Mann= 3 , 0 , 0
       0     0.1       0   462.9   0.045       0   477.9     0.1       0
Bank Sta=   462.9,   477.9
Exp/Cntr=0.3,0.1

Type RM Length L Ch R = 1 ,1229,499.309,494.657,489.069
XS GIS Cut Line= 3
     1805201.722      357133.854     1805071.153      357564.282
     1804989.433      358041.458
#Sta/Elev= 30
       0 1127.63    29.3 1118.61    48.9 1114.99    88.0 1101.44   107.6 1092.08
   156.5 1079.55   176.0 1078.53   352.0 1028.26   400.9 1015.36   420.5 1012.31
   440.0 1002.54   459.5  997.67   462.1  997.78   477.1  998.80   527.3 1001.91
   536.9 1004.43   556.3 1018.13   575.7 1028.38   595.0 1046.16   604.7 1051.85
   614.4 1055.25   633.8 1066.13   653.1 1072.85   682.2 1091.56   691.9 1094.25
   720.9 1112.13   730.6 1113.43   759.6 1123.16   779.0 1125.43   933.9 1117.45
#Mann= 3 , 0 , 0
       0     0.1       0   462.1   0.045       0   477.1     0.1       0
Bank Sta=   462.1,   477.1
Exp/Cntr=0.3,0.1

Type RM Length L Ch R = 1 ,734.4,361.897,359.336,362.933
XS GIS Cut Line= 3
     1804690.749      357054.721     1804593.235      357347.265
     1804742.362      358020.390
#Sta/Elev= 30
       0 1126.55     9.6 1125.62    48.2 1106.78    77.1 1090.15    96.4 1084.19
   115.6 1075.17   154.2 1065.74   183.1 1062.90   221.6 1053.43   250.5 1044.10
   279.5 1037.68   308.4 1034.24   366.6 1021.22   454.0 1009.37   463.7 1006.37
   483.2  993.87   492.9  989.28   508.3  987.33   522.0  986.39   523.3  986.47
   541.4  988.04   570.6  994.26   657.9 1001.66   716.2 1020.54   735.6 1025.13
   764.8 1035.75   842.4 1054.78   881.3 1060.07   939.6 1064.21   997.8 1070.90
#Mann= 3 , 0 , 0
       0     0.1       0   508.3   0.045       0   523.3     0.1       0
Bank Sta=   508.3,   523.3
Exp/Cntr=0.3,0.1

Type RM Length L Ch R = 1 ,375,365.702,375.023,377.174
XS GIS Cut Line= 4
     1804466.285      357111.714     1804314.491      357593.125
     1804261.271      357731.098     1804265.420      357853.510
#Sta/Elev= 30
       0 1057.60    38.8 1050.04    58.2 1044.75    77.7 1042.04   106.8 1035.33
   135.9 1033.39   155.3 1030.90   184.4 1022.25   194.1 1020.59   223.3 1013.33
   233.0 1012.50   262.1 1012.76   281.5 1011.18   310.6 1001.42   320.3  999.56
   349.5  988.61   368.9  985.06   388.3  983.32   475.7  979.60   491.4  981.43
   506.4  985.60   514.0  987.63   532.5  989.65   560.2  996.40   569.5  997.12
   588.0 1000.60   597.2 1001.37   643.4 1004.76   709.2 1007.03   775.1 1006.43
#Mann= 3 , 0 , 0
       0     0.1       0   491.4   0.045       0   506.4     0.1       0
Bank Sta=   491.4,   506.4
Exp/Cntr=0.3,0.1